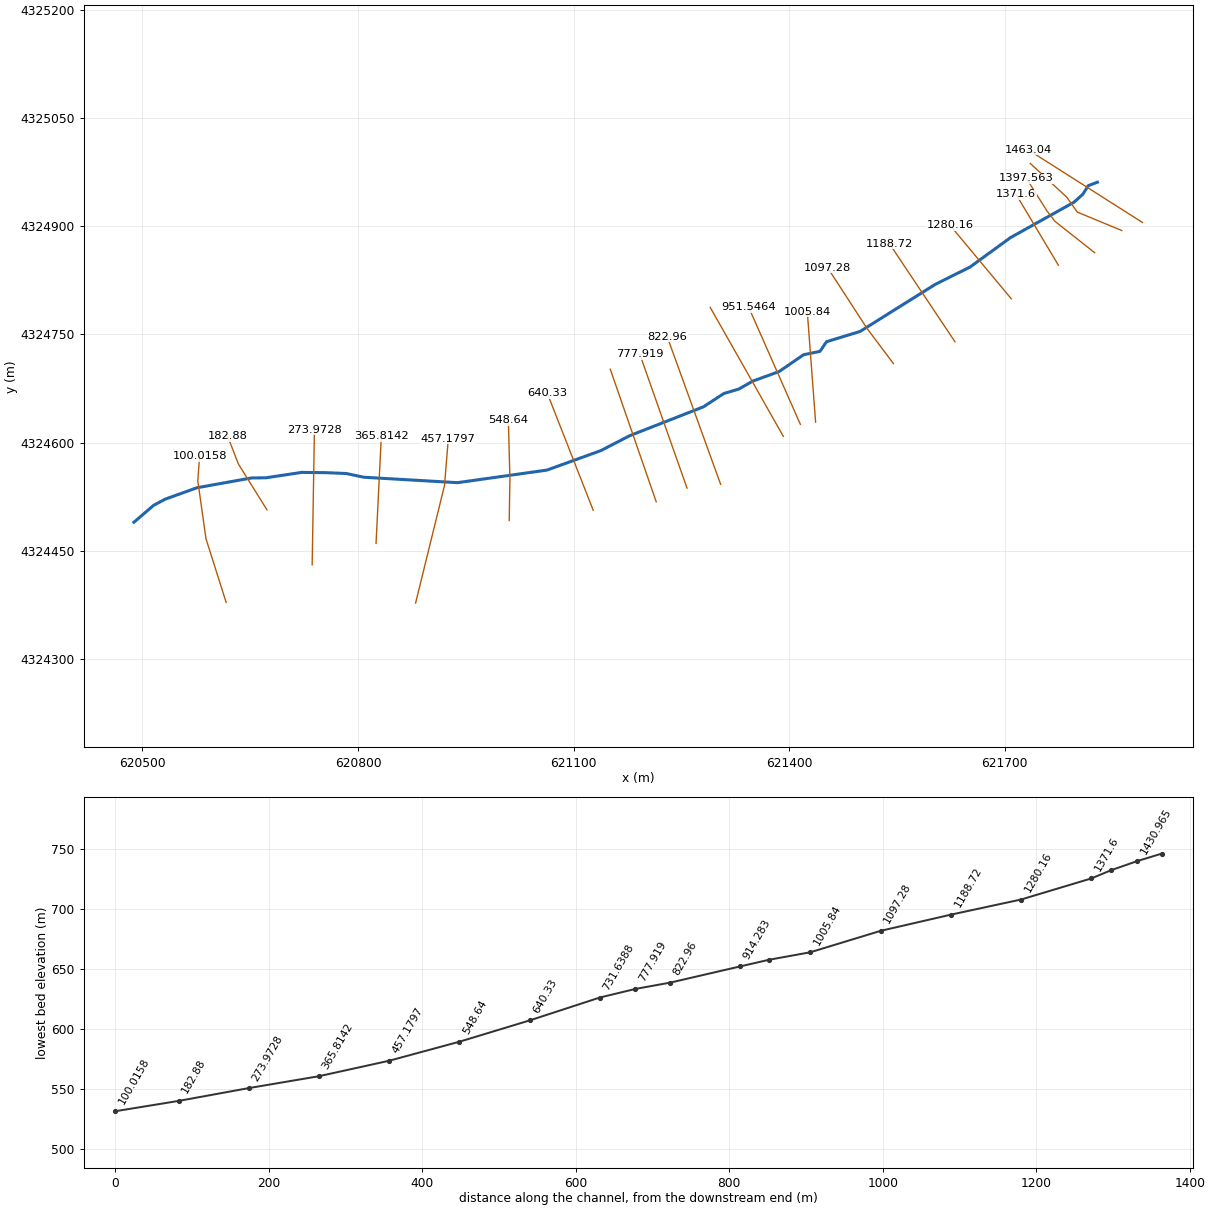
--- LaurelRunDry.prj (project) ---

Proj Title=LaurelRunDry
Current Plan=p01
Default Exp/Contr=0.3,0.1
SI Units
Geom File=g01
Flow File=f01
Plan File=p01
Background Map Layer=Google Hybrid
Y Axis Title=Elevation
X Axis Title(PF)=Main Channel Distance
X Axis Title(XS)=Station
BEGIN DESCRIPTION:
September 2018
Tucker County ABFE Study
US Army Corps of Engineers, Pittsburgh District
NAD 1983 UTM 17N (meters)
END DESCRIPTION:
DSS Export Rating Curves= 0
DSS Export Rating Curve Sorted= 0
DSS Export Volume Flow Curves= 0
DXF OffsetX= 0
DXF OffsetY= 0
DXF ScaleX= 1
DXF ScaleY= 10

--- LaurelRunDry.p01 (plan) ---

Plan Title=LaurelRunDry_plan
Program Version=5.05
Short Identifier=Plan1_subcritical
Geom File=g01
Flow File=f01
Subcritical Flow
K Sum by GR= 0
Std Step Tol= 0.003
Critical Tol= 0.003
Num of Std Step Trials= 20
Max Error Tol= 0.1
Flow Tol Ratio= 0.001
Split Flow NTrial= 30
Split Flow Tol= 0.006
Split Flow Ratio= 0.02
Log Output Level= 0
Friction Slope Method= 1
Unsteady Friction Slope Method= 2
Unsteady Bridges Friction Slope Method= 1
Parabolic Critical Depth
Global Vel Dist= 0 , 0 , 0
Global Log Level= 0
CheckData=True
Encroach Param=-1 ,0,0, 0
Computation Interval=1MIN
Output Interval=1HOUR
Instantaneous Interval=1HOUR
Mapping Interval=1HOUR
Computation Time Step Use Courant=        0
Computation Time Step Use Time Series=    0
Computation Time Step Count To Double=0
Computation Time Step Max Doubling=0
Computation Time Step Max Halving=0
Computation Time Step Residence Courant=0
Run HTab= 0
Run UNet= 0
Run Sediment= 0
Run PostProcess= 0
Run WQNet= 0
Run RASMapper=-1
UNET Theta= 1
UNET Theta Warmup= 1
UNET ZTol= 0.006
UNET ZSATol= 0.006
UNET MxIter= 20
UNET Max Iter WO Improvement= 0
UNET MaxInSteps= 0
UNET DtIC= 0
UNET DtMin= 0
UNET MaxCRTS= 20
UNET WFStab= 2
UNET SFStab= 1
UNET WFX= 1
UNET SFX= 1
UNET 1D Methodology=Finite Difference
UNET DSS MLevel= 4
UNET Pardiso=0
UNET DZMax Abort= 30
UNET Use Existing IB Tables=-1
UNET Froude Reduction=False
UNET Froude Limit= 0.8
UNET Froude Power= 4
UNET D1 Cores= 0
UNET D2 Coriolis=0
UNET D2 Cores= 0
UNET D2 Theta= 1
UNET D2 Theta Warmup= 1
UNET D2 Z Tol= 0.003
UNET D2 Volume Tol= 0.003
UNET D2 Max Iterations= 20
UNET D2 Equation= 0
UNET D2 RampUpFraction=0.1
UNET D2 TimeSlices= 1
UNET D2 BCVolumeCheck=0
UNET D1D2 MaxIter= 0
UNET D1D2 ZTol=0.003
UNET D1D2 QTol=0.1
UNET D1D2 MinQTol=0.03
Write IC File= 0
Write IC File at Fixed DateTime=0
Write IC File at Sim End=0
Echo Input=False
Echo Parameters=False
Echo Output=False
Write Detailed= 0
HDF Write Warmup=0
HDF Write Time Slices=0
HDF Flush=0
HDF Face Node Velocities=0
HDF Compression= 1
HDF Chunk Size= 1
HDF Spatial Parts= 1
HDF Use Max Rows=0
HDF Fixed Rows= 1
Calibration Method= 0
Calibration Iterations= 20
Calibration Max Change=0.05
Calibration Tolerance=0.2
Calibration Maximum=1.5
Calibration Minimum=0.5
Calibration Optimization Method= 1
WQ AD Non Conservative
WQ ULTIMATE=-1
WQ Max Comp Step=1HOUR
WQ Output Interval=15MIN
WQ Output Selected Increments= 0
WQ Output face flow=0
WQ Output face velocity=0
WQ Output face area=0
WQ Output face dispersion=0
WQ Output cell volume=0
WQ Output cell surface area=0
WQ Output cell continuity=0
WQ Output cumulative cell continuity=0
WQ Output face conc=0
WQ Output face dconc_dx=0
WQ Output face courant=0
WQ Output face peclet=0
WQ Output face adv mass=0
WQ Output face disp mass=0
WQ Output cell mass=0
WQ Output cell source sink temp=0
WQ Output nsm pathways=0
WQ Output nsm derived pathways=0
WQ Output MaxMinRange=-1
WQ Daily Max Min Mean=-1
WQ Daily Range=0
WQ Daily Time=0
WQ Create Restart=0
WQ Fixed Restart=0
WQ System Summary=0
WQ Write To DSS=0
WQ Use Fixed Temperature=0
Sorting and Armoring Iterations= 10
XS Update Threshold= 0.02
Bed Roughness Predictor= 0
Hydraulics Update Threshold= 0.02
Energy Slope Method= 1
Volume Change Method= 1
Sediment Retention Method= 0
XS Weighting Method= 0
Number of US Weighted Cross Sections= 1
Number of DS Weighted Cross Sections= 1
Upstream XS Weight=0
Main XS Weight=1
Downstream XS Weight=0
Number of DS XS's Weighted with US Boundary= 1
Upstream Boundary Weight= 1
Weight of XSs Associated with US Boundary= 0
Number of US XS's Weighted with DS Boundary= 1
Downstream Boundary Weight= 0.5
Weight of XSs Associated with DS Boundary= 0.5
Percentile Method= 0
Sediment Output Level= 4
Mass or Volume Output= 0
Output Increment Type= 1
Profile and TS Output Increment= 1
XS Output Flag= 0
XS Output Increment= 10
Write Gradation File= 0
Read Gradation Hotstart= 0
Write HDF5 File= 1
Write Binary Output= 1
Write DSS Sediment File= 0
SV Curve= 0
Specific Gage Flag= 0

--- LaurelRunDry.f01 (steady flow) ---

Flow Title=LaurelRunDry_flow
Program Version=5.05
Number of Profiles= 1
Profile Names=PF 1
River Rch & RM=Laurel Run (Dry),1               ,1463.04
   14.64
River Rch & RM=Laurel Run (Dry),1               ,640.33
  16.282
River Rch & RM=Laurel Run (Dry),1               ,365.8142
 17.0466
River Rch & RM=Laurel Run (Dry),1               ,100.0158
 18.4341
Boundary for River Rch & Prof#=Laurel Run (Dry),1               , 1
Up Type= 2
Dn Type= 1
Dn Known WS=530.4
DSS Import GetInterval= 0
DSS Import GetPeak= 0
DSS Import FillOption= 0

--- LaurelRunDry.g01 (geometry) ---

Geom Title=LaurelRunDry_geometry
Program Version=5.05

River Reach=Laurel Run (Dry),1
Reach XY= 30
     621828.9593    4324960.8794     621816.2593    4324956.1169
     621808.7187    4324944.2106     621796.3908    4324933.1155
     621708.1768    4324884.1942     621651.6394     4324843.258
      621603.137    4324819.1947     621498.7587    4324754.1071
     621452.0674    4324739.9129     621442.9693    4324726.4959
     621420.0781    4324721.8114      621386.046    4324698.5445
     621349.3934    4324685.2929     621330.0163     4324674.293
     621309.0194    4324668.0685     621280.8739    4324649.7288
      621178.083    4324609.6443     621137.9986    4324589.0068
     621062.9891    4324562.0192     620938.5027    4324544.5926
     620808.2007    4324552.1265     620783.7547     4324557.277
     620755.8072    4324558.4473     620721.6759    4324558.8442
     620672.0624    4324551.3598     620651.63334324551.08122373
620575.8328651894324537.53074992620531.9191525454324521.79163793
620515.5229288174324513.15364458     620488.3129    4324489.7878

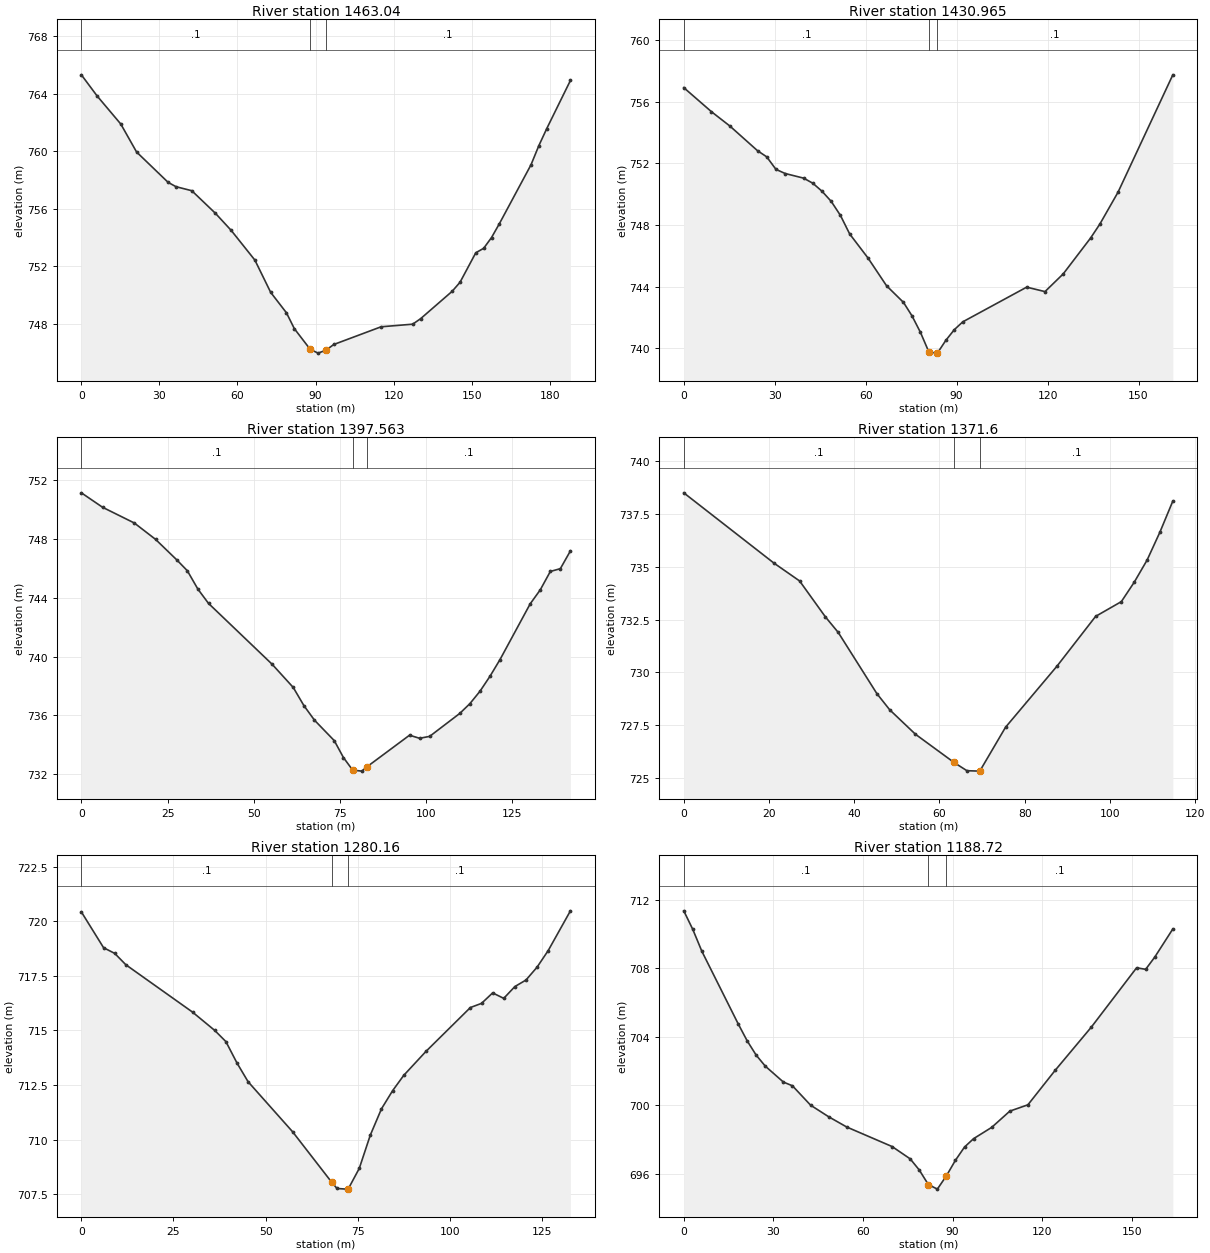
Type RM Length L Ch R = 1 ,1463.04 ,33.98,32.08,30.6
XS GIS Cut Line= 2
     621891.7132    4324905.0593     621732.8996    4325005.6405
#Sta/Elev= 30
       0  765.31    6.06  763.84   15.16  761.89   21.22  759.95   33.35  757.84
   36.38  757.54   42.45  757.26   51.54  755.69   57.61   754.5    66.7  752.44
   72.77   750.2   78.83  748.78   81.86  747.68   87.93  746.25   90.96  745.98
   93.99  746.18   97.02  746.58  115.22  747.81  127.34  747.99  130.38  748.37
   142.5  750.27  145.54   750.9   151.6  752.95  154.63  753.26  157.66  754.01
   160.7  754.98  172.82  759.06  175.86   760.4  178.89  761.58  187.98  764.92
#Mann= 3 , 0 , 0
       0      .1       0   87.93      .1       0   93.99      .1       0
Bank Sta=87.93,93.99
XS Rating Curve= 0 ,0
Exp/Cntr=0.3,0.1

Type RM Length L Ch R = 1 ,1430.965,33.47,33.4,33.34
XS GIS Cut Line= 4
     621862.8852    4324893.9698     621801.0388     4324919.436
     621786.4866    4324939.9412     621735.5543    4324986.9049
#Sta/Elev= 30
       0   756.9    9.12  755.34    15.2  754.41   24.32  752.81   27.36  752.41
    30.4   751.6   33.44  751.33   39.52  751.03   42.56   750.7    45.6  750.18
   48.64  749.52   51.68  748.61   54.72  747.41    60.8  745.84   66.88  744.05
   72.47  742.97   75.27   742.1   78.06  741.03   80.85  739.75   83.65  739.68
   86.44  740.51   89.23   741.2   92.03  741.71  113.11  743.96  119.14  743.67
  125.16  744.82   134.2  747.15  137.21  748.04  143.24  750.12  161.31  757.73
#Mann= 3 , 0 , 0
       0      .1       0   80.85      .1       0   83.65      .1       0
Bank Sta=80.85,83.65
XS Rating Curve= 0 ,0
Exp/Cntr=0.3,0.1

Type RM Length L Ch R = 1 ,1397.563,26.34,25.96,25.59
XS GIS Cut Line= 4
      621825.182    4324863.2119     621769.6194    4324906.8682
     621758.3746    4324921.7511     621730.2626    4324966.0689
#Sta/Elev= 30
       0  751.12    6.14  750.14   15.36  749.07   21.51  747.96   27.65  746.57
   30.72  745.83   33.79  744.58   36.87  743.61    55.3  739.48   61.44   737.9
   64.52  736.67   67.59  735.68   73.33  734.29   75.99  733.14   78.66  732.29
   81.32  732.22   82.73   732.5   95.15  734.66   98.06  734.45  100.98  734.58
  109.72  736.14  112.64   736.8  115.56  737.64  118.47  738.66  121.39   739.8
  130.13  743.58  133.05  744.53  135.97  745.78  138.88  745.97   141.8  747.18
#Mann= 3 , 0 , 0
       0      .1       0   78.66      .1       0   82.73      .1       0
Bank Sta=78.66,82.73
XS Rating Curve= 0 ,0
Exp/Cntr=0.3,0.1

Type RM Length L Ch R = 1 ,1371.6  ,90.89,91.44,92.23
XS GIS Cut Line= 2
     621774.6393    4324845.9586     621715.5983    4324944.3605
#Sta/Elev= 19
       0  738.51   21.14  735.18   27.18  734.33   33.22  732.63   36.24  731.89
    45.3  728.99   48.32  728.22   54.36  727.06   63.42  725.72   66.44  725.33
   69.46  725.31    75.5  727.39   87.58  730.29   96.64  732.65  102.68  733.35
   105.7  734.27  108.72  735.32  111.74  736.65  114.76  738.12
#Mann= 3 , 0 , 0
       0      .1       0   63.42      .1       0   69.46      .1       0
Bank Sta=63.42,69.46
XS Rating Curve= 0 ,0
Exp/Cntr=0.3,0.1

Type RM Length L Ch R = 1 ,1280.16 ,91.81,91.44,91.07
XS GIS Cut Line= 2
     621709.1804    4324799.3168      621624.002    4324901.1153
#Sta/Elev= 29
       0  720.43    6.03  718.79    9.05  718.53   12.07  718.01   30.17  715.84
    36.2     715   39.22  714.49   42.23  713.51   45.25  712.65   57.32  710.36
   67.92  708.05   69.38  707.76   71.92  707.73    72.4  707.73   75.42  708.68
   78.43  710.21   81.45  711.41   84.47  712.24   87.48  712.94   93.52  714.04
  105.58  716.05   108.6  716.24  111.62  716.72  114.63  716.47  117.65  717.01
  120.67  717.31  123.68   717.9   126.7  718.66  132.73  720.48
#Mann= 3 , 0 , 0
       0      .1       0   67.92      .1       0    72.4      .1       0
Bank Sta=67.92,72.4
XS Rating Curve= 0 ,0
Exp/Cntr=0.3,0.1

Type RM Length L Ch R = 1 ,1188.72 ,91.28,91.44,91.39
XS GIS Cut Line= 2
     621630.7716     4324739.806     621539.5264    4324875.8131
#Sta/Elev= 30
       0  711.36    3.03  710.27    6.07  708.99    18.2  704.76   21.23  703.76
   24.26  702.92    27.3  702.28   33.36  701.35    36.4  701.13   42.46     700
   48.53  699.32   54.59  698.72   69.76  697.58   75.82  696.86   78.86  696.21
   81.89  695.36   84.92  695.09   87.96  695.87   90.99  696.78   94.02  697.55
   97.05  698.04  103.12   698.7  109.19  699.65  115.25  700.02  124.35  702.03
  136.48  704.56  151.65  708.03  154.68  707.94  157.71  708.65  163.78   710.3
#Mann= 3 , 0 , 0
       0      .1       0   81.89      .1       0   87.96      .1       0
Bank Sta=81.89,87.96
XS Rating Curve= 0 ,0
Exp/Cntr=0.3,0.1

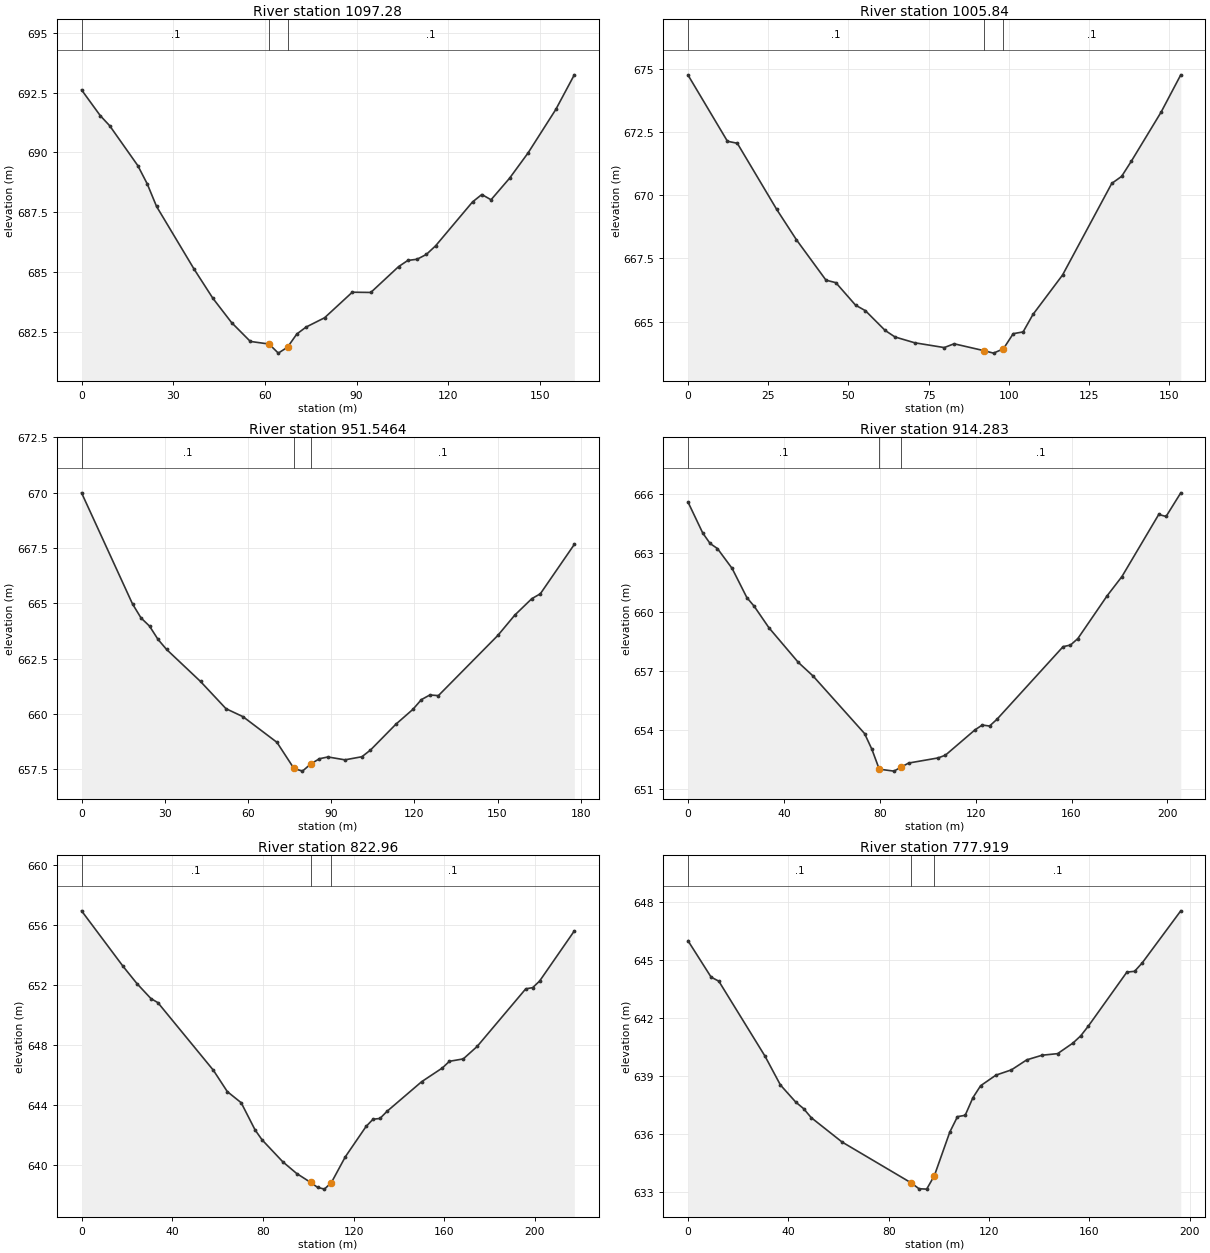
Type RM Length L Ch R = 1 ,1097.28 ,96.42,91.44,89.36
XS GIS Cut Line= 3
     621545.1851    4324709.5327     621508.2626     4324758.515
     621453.7426    4324842.1749
#Sta/Elev= 30
       0  692.62    6.13  691.54     9.2  691.12    18.4  689.45   21.47  688.69
   24.54  687.74    36.8  685.12   42.94   683.9   49.07  682.88   55.21  682.09
   61.34  681.98   64.37   681.6   67.39  681.85   70.42   682.4   73.44  682.69
    79.5  683.08   88.57  684.15   94.63  684.14   103.7  685.22  106.73  685.48
  109.76  685.53  112.78  685.73  115.81  686.09  127.91  687.93  130.94  688.24
  133.96  688.02  140.01  688.92  146.07  689.98  155.14   691.8   161.2  693.25
#Mann= 3 , 0 , 0
       0      .1       0   61.34      .1       0   67.39      .1       0
Bank Sta=61.34,67.39
XS Rating Curve= 0 ,0
Exp/Cntr=0.3,0.1

Type RM Length L Ch R = 1 ,1005.84 ,53.07,54.29,55.53
XS GIS Cut Line= 2
     621436.8254    4324628.5151     621425.2617     4324781.735
#Sta/Elev= 26
       0  674.76   12.29  672.14   15.37  672.06   27.66  669.44    33.8  668.24
   43.02  666.64    46.1  666.54   52.24  665.65   55.32  665.43   61.46  664.65
   64.54  664.39   70.68  664.16    79.9  663.97   82.97  664.12   92.19  663.85
   95.27  663.75   98.34  663.92  101.41  664.52  104.49  664.59  107.56  665.28
  116.78  666.84  132.14  670.47  135.22  670.75  138.29  671.36  147.51  673.29
  153.66  674.77
#Mann= 3 , 0 , 0
       0      .1       0   92.19      .1       0   98.34      .1       0
Bank Sta=92.19,98.34
XS Rating Curve= 0 ,0
Exp/Cntr=0.3,0.1

Type RM Length L Ch R = 1 ,951.5464,36.91,37.26,37.62
XS GIS Cut Line= 2
     621415.6062    4324625.4172     621343.6394    4324787.8717
#Sta/Elev= 28
       0  669.99   18.38  664.97   21.44  664.34   24.51  663.97   27.57  663.37
   30.63  662.92   42.89  661.47   52.08  660.24   58.21  659.88   70.46  658.72
   76.59  657.54   79.65  657.42   82.71  657.75   85.78  657.98   88.84  658.06
   94.97  657.93  101.09  658.07  104.16  658.37  113.35  659.54  119.48  660.21
  122.54  660.65   125.6  660.86  128.67  660.83  150.11  663.55  156.24  664.47
  162.36  665.21  165.43  665.43  177.68  667.66
#Mann= 3 , 0 , 0
       0      .1       0   76.59      .1       0   82.71      .1       0
Bank Sta=76.59,82.71
XS Rating Curve= 0 ,0
Exp/Cntr=0.3,0.1

Type RM Length L Ch R = 1 ,914.283 ,91.91,91.32,90.73
XS GIS Cut Line= 2
     621391.9474    4324608.7708     621290.2263    4324787.4037
#Sta/Elev= 30
       0  665.57    6.14     664     9.2  663.47   12.27  663.21   18.41   662.2
   24.55  660.72   27.61  660.28   33.75  659.19   46.02  657.43   52.16  656.74
   73.64  653.82    76.7  653.02   79.77  652.01   85.91  651.91   88.98  652.12
   92.04  652.32  104.32  652.58  107.38  652.72  119.66     654  122.73  654.25
  125.79   654.2  128.86  654.54  156.47  658.23  159.54  658.31  162.61  658.64
  174.88  660.82  181.02  661.79  196.36  664.94  199.43  664.84  205.56  666.04
#Mann= 3 , 0 , 0
       0      .1       0   79.77      .1       0   88.98      .1       0
Bank Sta=79.77,88.98
XS Rating Curve= 0 ,0
Exp/Cntr=0.3,0.1

Type RM Length L Ch R = 1 ,822.96  ,45.07,45.04,45.01
XS GIS Cut Line= 2
     621304.7289    4324542.2488       621230.43    4324746.5719
#Sta/Elev= 30
       0  656.92   18.37  653.21    24.5  652.06   30.62  651.07   33.68   650.8
   58.18  646.29   64.31  644.87   70.43  644.13   76.55  642.32   79.62  641.66
    88.8  640.19   94.93  639.41  101.05  638.82  104.11  638.49  107.16  638.37
  110.24  638.81  116.36  640.52  125.55  642.55  128.61  643.03  131.67  643.08
  134.73  643.55  150.05  645.53  159.23  646.45  162.29  646.89  168.42  647.05
  174.54  647.88  195.98  651.72  199.04   651.8   202.1  652.24  217.41  655.58
#Mann= 3 , 0 , 0
       0      .1       0  101.05      .1       0  110.24      .1       0
Bank Sta=101.05,110.24
XS Rating Curve= 0 ,0
Exp/Cntr=0.3,0.1

Type RM Length L Ch R = 1 ,777.919 ,46.3,46.28,46.26
XS GIS Cut Line= 2
     621257.9142    4324537.0462     621192.2974    4324722.2549
#Sta/Elev= 30
       0  645.98    9.21   644.1   12.28  643.89    30.7  640.01   36.84  638.52
   42.98  637.63   46.05   637.3   49.12  636.83    61.4  635.57   89.03  633.45
    92.1  633.15   95.17  633.13   98.24  633.83  104.38  636.08  107.45  636.88
  110.52  636.95   113.6  637.86  116.67  638.48  122.81  639.03  128.95   639.3
  135.09  639.82  141.23  640.06  147.37  640.14  153.51  640.69  156.58  641.06
  159.65  641.57     175  644.36  178.07   644.4  181.14  644.84  196.49  647.53
#Mann= 3 , 0 , 0
       0      .1       0   89.03      .1       0   98.24      .1       0
Bank Sta=89.03,98.24
XS Rating Curve= 0 ,0
Exp/Cntr=0.3,0.1

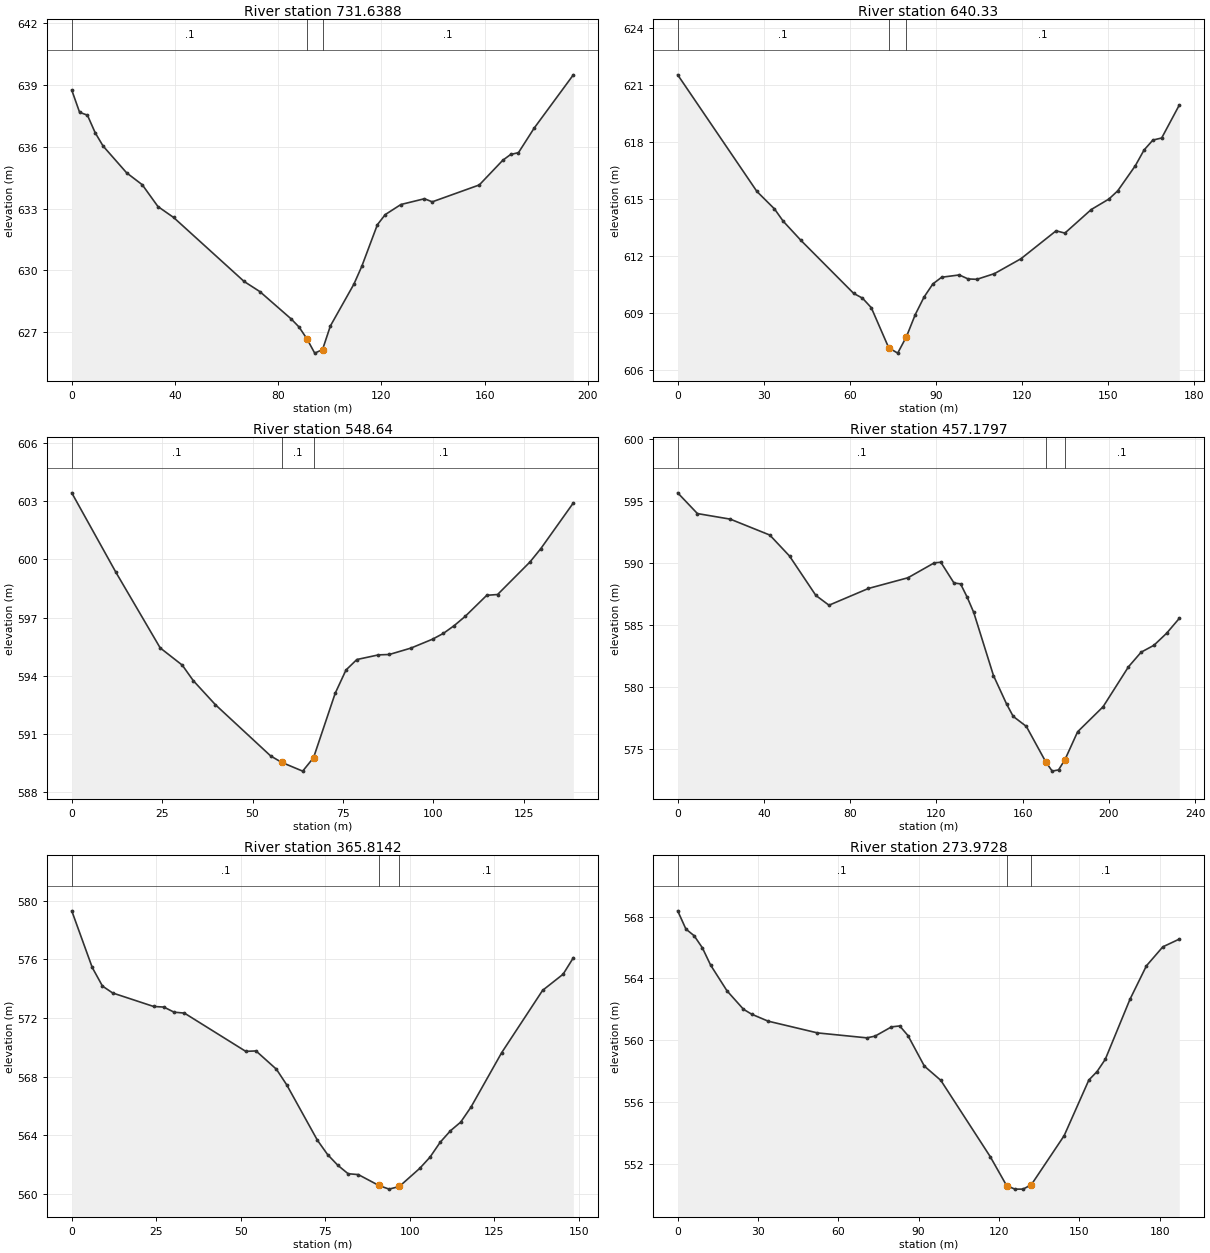
Type RM Length L Ch R = 1 ,731.6388,91.16,91.31,92.18
XS GIS Cut Line= 2
     621215.0332    4324518.1559     621151.1434    4324701.7227
#Sta/Elev= 30
       0  638.76    3.04  637.68    6.07  637.54    9.11  636.68   12.15  636.04
   21.26  634.74   27.33  634.16   33.41   633.1   39.48  632.57   66.81  629.46
   72.89  628.97   85.04  627.64   88.07  627.25   91.11  626.68   94.15  625.98
   97.18  626.15  100.22   627.3  109.33  629.33  112.37  630.19  118.44  632.22
  121.48  632.71  127.55   633.2  136.66  633.48   139.7  633.33  157.92  634.15
  167.03  635.35  170.07  635.63  173.11  635.72  179.18  636.91  194.37   639.5
#Mann= 3 , 0 , 0
       0      .1       0   91.11      .1       0   97.18      .1       0
Bank Sta=91.11,97.18
XS Rating Curve= 0 ,0
Exp/Cntr=0.3,0.1

Type RM Length L Ch R = 1 ,640.33  ,94.29,91.69,90.58
XS GIS Cut Line= 2
     621127.3648    4324506.3707     621063.3015    4324668.9143
#Sta/Elev= 30
       0  621.53   27.59   615.4   33.72  614.48   36.78  613.83   42.91  612.83
    61.3  610.04   64.37  609.79   67.43  609.29   73.51  607.18   76.63   606.9
   79.69  607.77   82.76  608.93   85.82  609.85   88.89  610.54   91.95  610.89
   98.08  611.01  101.15   610.8  104.21  610.78  110.34  611.08  119.54  611.86
   131.8  613.33  134.87  613.21  144.06  614.45  150.19     615  153.26  615.43
  159.39  616.75  162.45  617.58  165.52   618.1  168.58  618.21  174.71  619.94
#Mann= 3 , 0 , 0
       0      .1       0   73.51      .1       0   79.69      .1       0
Bank Sta=73.51,79.69
XS Rating Curve= 0 ,0
Exp/Cntr=0.3,0.1

Type RM Length L Ch R = 1 ,548.64  ,94,91.46,91.63
XS GIS Cut Line= 4
     621010.4902    4324492.1059     621011.5402    4324553.2474
     621011.2996    4324555.9691     621009.3264    4324630.8142
#Sta/Elev= 25
       0  603.43   12.23  599.33   24.46  595.44   30.58  594.55   33.63  593.75
   39.75  592.51   55.04  589.87   58.09  589.54   63.88  589.09   66.88  589.78
   72.87   593.1   75.86   594.3   78.86  594.84   84.85  595.08   87.84   595.1
   93.83  595.43   99.82  595.89  102.82  596.19  105.81  596.59  108.81  597.06
   114.8  598.15  117.79  598.19  126.77  599.87  129.77  600.56  138.75  602.91
#Mann= 3 , 0 , 0
       0      .1       0   58.09      .1       0   66.88      .1       0
Bank Sta=58.09,66.88
XS Rating Curve= 0 ,0
Exp/Cntr=0.3,0.1

Type RM Length L Ch R = 1 ,457.1797,90.97,91.37,91.48
XS GIS Cut Line= 3
     620880.2095     4324377.872     620920.4534    4324540.7944
     620925.7179    4324605.4141
#Sta/Elev= 30
       0  595.64    9.15  593.97   24.41  593.52   42.72  592.24   51.87  590.55
   64.08  587.38   70.18  586.59   88.49  587.94  106.79   588.8     119     590
  122.05  590.05  128.15  588.38   131.2  588.31  134.26  587.24  137.31  586.01
  146.46  580.93  152.56  578.63  155.61  577.64  161.72  576.83  170.77  573.96
  173.71  573.23  176.66  573.33  179.61  574.15   185.5   576.4  197.29  578.41
  209.08  581.63  214.97  582.81  220.87  583.36  226.76  584.33  232.65  585.53
#Mann= 3 , 0 , 0
       0      .1       0  170.77      .1       0  179.61      .1       0
Bank Sta=170.77,179.61
XS Rating Curve= 0 ,0
Exp/Cntr=0.3,0.1

Type RM Length L Ch R = 1 ,365.8142,92.93,91.84,94.8
XS GIS Cut Line= 2
     620825.1761    4324460.4222     620832.4976    4324608.6468
#Sta/Elev= 30
       0   579.3    6.06  575.44    9.09  574.17   12.11   573.7   24.23  572.78
   27.26  572.74   30.29  572.39   33.32  572.33   51.49  569.72   54.52  569.75
   60.57   568.5    63.6  567.44   72.69  563.66   75.72  562.68   78.75  561.95
   81.77  561.38    84.8  561.32   90.86  560.58   93.89  560.33   96.92  560.51
  102.98  561.75     106  562.51  109.03  563.53  112.06  564.31  115.09   564.9
  118.12  565.92   127.2  569.63  139.32  573.88  145.38  574.98  148.41   576.1
#Mann= 3 , 0 , 0
       0      .1       0   90.86      .1       0   96.92      .1       0
Bank Sta=90.86,96.92
XS Rating Curve= 0 ,0
Exp/Cntr=0.3,0.1

Type RM Length L Ch R = 1 ,273.9728,89.05,91.09,93.13
XS GIS Cut Line= 2
     620736.2759    4324430.7888     620739.4509    4324618.1142
#Sta/Elev= 30
       0  568.37    3.07  567.19    6.14  566.76    9.21  565.98   12.29  564.86
   18.43  563.19   24.57     562   27.64  561.68   33.78  561.23   52.21  560.47
   70.64  560.15   73.71  560.26   79.86  560.86   82.93  560.92      86   560.3
   92.14  558.32   98.28   557.4  116.71  552.47  122.85  550.59  125.93  550.36
     129  550.36  132.07  550.64  144.35  553.82  153.57  557.42  156.64  557.97
  159.71  558.76  168.92  562.64  175.07  564.81  181.21  566.04  187.35  566.54
#Mann= 3 , 0 , 0
       0      .1       0  122.85      .1       0  132.07      .1       0
Bank Sta=122.85,132.07
XS Rating Curve= 0 ,0
Exp/Cntr=0.3,0.1

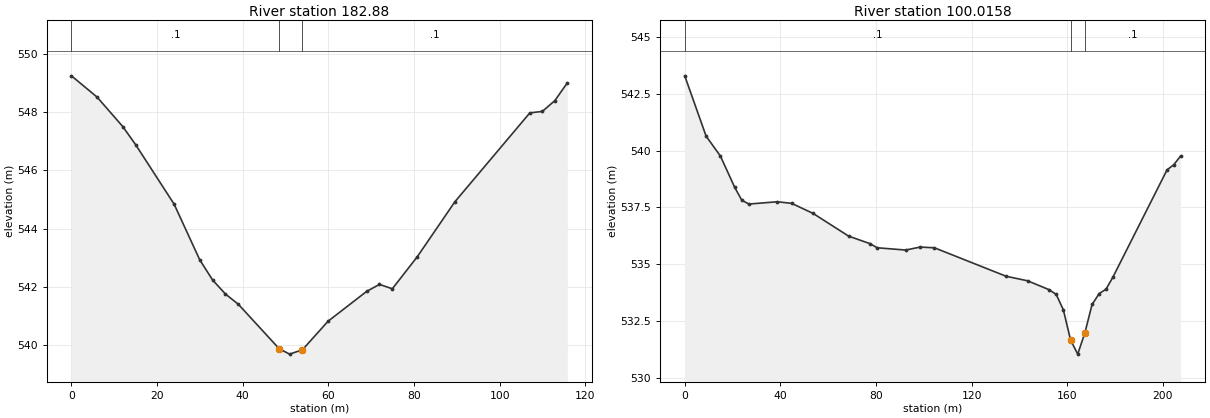
Type RM Length L Ch R = 1 ,182.88  ,84.45,82.86,81.28
XS GIS Cut Line= 3
     620673.3778    4324506.9701     620633.6126    4324570.4861
     620618.8007    4324608.5892
#Sta/Elev= 22
       0  549.24    5.99  548.51   11.99   547.5   14.99  546.88   23.98  544.84
   29.97  542.93   32.97  542.24   35.97  541.76   38.97  541.41   48.55  539.88
   50.96   539.7   53.95  539.85   59.95  540.83   68.94  541.85   71.94  542.09
   74.94  541.94   80.78  543.04   89.54  544.92  107.06  547.97  109.98  548.02
   112.9  548.39  115.82     549
#Mann= 3 , 0 , 0
       0      .1       0   48.55      .1       0   53.95      .1       0
Bank Sta=48.55,53.95
XS Rating Curve= 0 ,0
Exp/Cntr=0.3,0.1

Type RM Length L Ch R = 1 ,100.0158,131.46,191.46,135.38
XS GIS Cut Line= 4
     620616.5567    4324378.8388     620588.5108    4324466.9453
     620577.1337    4324547.1142     620579.6422    4324581.0724
#Sta/Elev= 30
       0  543.28    8.95  540.63   14.91  539.76   20.88  538.39   23.86  537.82
   26.84  537.65   38.77  537.75   44.74  537.68   53.69  537.24    68.6  536.24
   77.55  535.91   80.53  535.73   92.46  535.63   98.46  535.76  104.46  535.73
  134.45  534.48  143.45  534.28  152.44  533.89  155.44  533.68  158.44     533
  161.44  531.68  164.44  531.06  167.44     532  170.44  533.24  173.43  533.72
  176.27  533.91  179.11  534.43  201.81  539.15  204.65  539.38  207.49  539.76
#Mann= 3 , 0 , 0
       0      .1       0  161.44      .1       0  167.44      .1       0
Bank Sta=161.44,167.44
XS Rating Curve= 0 ,0
Exp/Cntr=0.3,0.1
LCMann Table=0

Chan Stop Cuts=-1
Use User Specified Reach Order=0
Composite Channel Slope=5